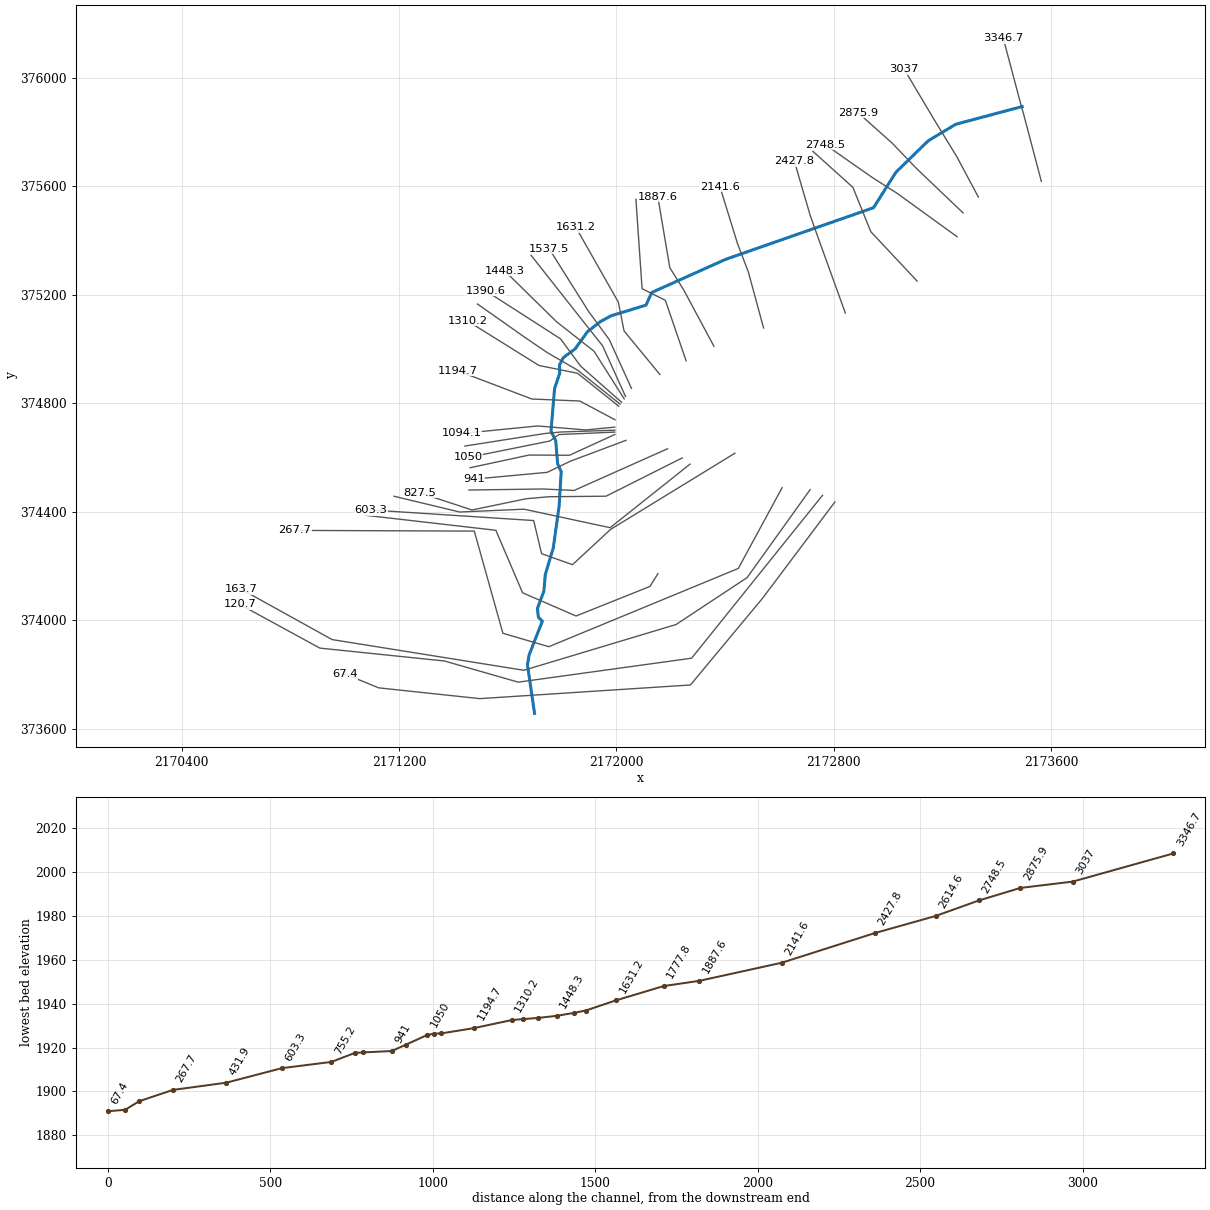
--- GrnbrRvT5.prj (project) ---

Proj Title=GrnbrRvT5
Current Plan=p01
Geom File=g01
Flow File=f01
Plan File=p01
DSS Export Rating Curves=0
DSS Export Rating Curve Sorted=0
DSS Export Volume Flow Curves=0
DXF OffsetX=0
DXF OffsetY=0
DXF ScaleX=0
DXF ScaleY=0

--- GrnbrRvT5.p01 (plan) ---

Plan Title=Floodplain
Program Version=4.00
Geom File=g01
Flow File=f01
K Sum by GR=0
Std Step Tol=0.01
Critical Tol=0.01
Num of Std Step Trials=20
Max Error Tol=0.3
Flow Tol Ratio=0.001
Split Flow NTrial=30
Split Flow Tol=0.02
Split Flow Ratio=0.02
Log Output Level=0
Friction Slope Method=1
Unsteady Friction Slope Method=2
Unsteady Bridges Friction Slope Method=1
Global Log Level=0
CheckData=False
Run HTab=0
Run UNet=0
Run PostProcess=0
UNET Theta=0
UNET Theta Warmup=0
UNET ZTol=0
UNET ZSATol=0
UNET MxIter=0
UNET MaxInSteps=0
UNET DtIC=0
UNET DtMin=0
UNET MaxCRTS=0
UNET WFStab=0
UNET SFStab=0
UNET WFX=0
UNET SFX=0
UNET DSS MLevel=0
UNET DZMax Abort=0
UNET Convert EG Bridges=0
UNET Use Existing IB Tables=0
UNET Froude Limit=0
UNET Froude Power=0
Write IC File=0
Echo Input=False
Echo Output=False
Write Detailed=0

--- GrnbrRvT5.f01 (steady flow) ---

Flow Title=NFF Regression Equation
Program Version=4.00
Number of Profiles=1
Profile Names=P100yr
River Rch & RM=GrnbrRvT5,Main      ,3346.7
521.2398
River Rch & RM=GrnbrRvT5,Main      ,1777.8
537.6899
River Rch & RM=GrnbrRvT5,Main      ,267.7
596.3137
Boundary for River Rch & Prof#=GrnbrRvT5,Main      ,1
Up Type=0
Dn Type=3
Dn Slope=0.047321

--- GrnbrRvT5.g01 (geometry) ---

Geom Title=USGS 3m DEM
Program Version=4.10

River Reach=GrnbrRvT5       ,Main
Reach XY= 30
     2173493.218      375894.452     2173249.563       375829.27
        2173148.      375768.332      2173029.25      375652.707
     2172946.437      375521.457     2172402.401      375331.121
     2172130.614      375208.956     2172108.938      375162.082
      2171980.44      375122.818     2171941.267      375101.358
     2171894.077      375064.578     2171848.275      375000.732
     2171805.038      374968.737     2171790.806      374941.745
       2171791.5      374910.516     2171772.763      374854.999
     2171759.577      374697.467     2171776.926      374662.075
     2171783.866       374577.41     2171797.052      374547.569
     2171789.418      374420.573     2171767.905      374267.205
     2171738.758      374169.355     2171733.206      374106.898
     2171709.611      374043.746     2171713.081       374011.13
     2171727.654      373996.556      2171679.25       373873.02
        2171673.       373835.52     2171698.984      373656.719

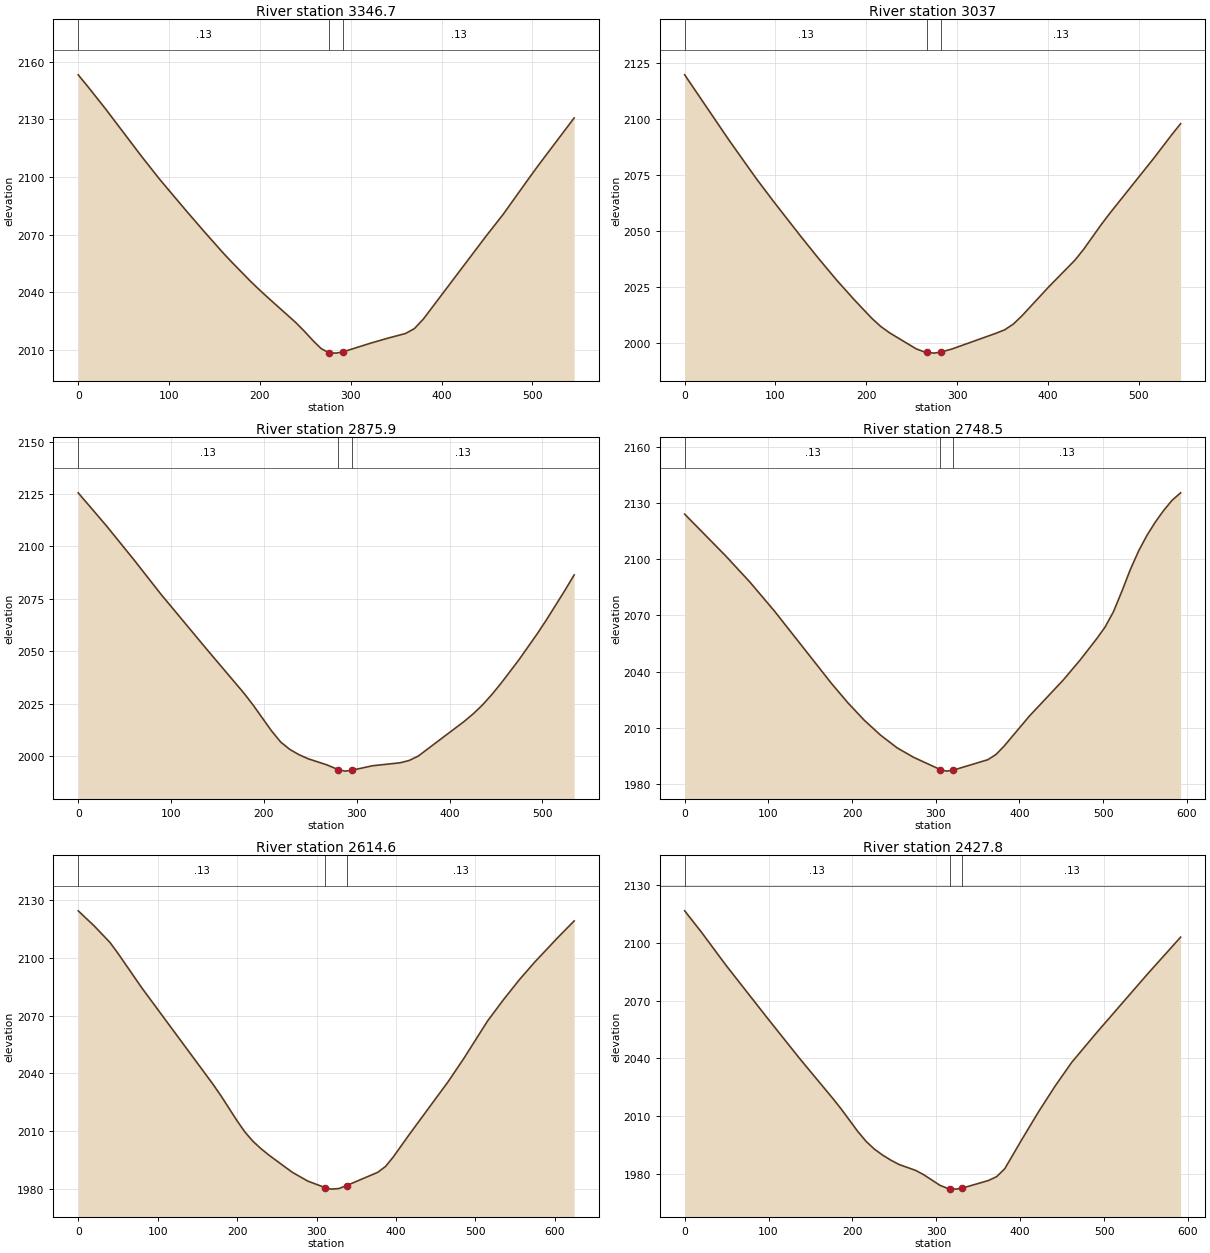
Type RM Length L Ch R = 1 ,3346.7  ,303.5,309.7,316.1
XS GIS Cut Line= 4
       2173564.1      375618.316     2173498.114      375868.995
     2173489.109      375900.577     2173423.929      376146.017
#Sta/Elev= 30
       0 2153.23      10 2147.49    29.9 2135.63    69.8 2110.78    89.7 2098.87
   119.6 2082.11   139.6 2071.19   159.5 2060.59   169.5 2055.57   189.4 2045.95
   199.4 2041.41   209.4 2037.09   239.3 2024.44   249.2 2019.72   259.2  2014.6
   267.4 2010.82   275.6  2008.7   276.3 2008.68   283.8 2008.43   291.3 2009.05
   321.4 2013.54   340.9 2016.21   360.4 2018.65   370.2 2021.21     380 2026.16
   448.3 2068.86   467.9 2080.67   497.2 2100.05   506.9 2106.33     546  2130.8
#Mann= 3 , 0 , 0
       0     .13       0   276.3     .05       0   291.3     .13       0
Bank Sta=276.3,291.3
XS Rating Curve= 0 ,0
Exp/Cntr=0.3,0.1

Type RM Length L Ch R = 1 ,3037    ,156.2,161.1,165.9
XS GIS Cut Line= 4
     2173332.352      375560.541     2173253.681      375708.347
     2173172.516      375841.356     2173058.689      376033.083
#Sta/Elev= 30
       0 2119.81    49.2 2090.44    78.8 2073.54    98.5 2062.97     128 2047.65
   147.7 2037.72   167.4 2028.18   186.9 2019.36   196.7 2015.14   206.4 2011.02
   216.1 2007.44   225.9 2004.59   255.1 1997.47   264.8 1996.02   267.1 1995.92
   274.6 1995.59   282.1 1996.05     294 1997.38   342.6 2004.42   352.3 2005.97
     362 2008.56   371.7 2012.34   400.8  2025.1   429.9 2037.13   439.6 2042.04
     459 2053.09   468.7 2058.24   517.1 2082.81   536.5 2093.11   546.2    2098
#Mann= 3 , 0 , 0
       0     .13       0   267.1     .05       0   282.1     .13       0
Bank Sta=267.1,282.1
XS Rating Curve= 0 ,0
Exp/Cntr=0.3,0.1

Type RM Length L Ch R = 1 ,2875.9  ,122,127.5,132.9
XS GIS Cut Line= 4
     2173275.955      375502.351     2173103.906      375666.772
     2173015.193      375759.477      2172890.05      375871.391
#Sta/Elev= 30
       0 2125.62    29.8 2110.18    59.5 2093.94    89.2 2077.15   138.8 2050.73
   178.5 2029.95   188.4 2024.28   208.2 2011.96   218.2 2006.56   228.1 2003.03
     238 2000.51   247.8  1998.6   267.6 1995.74   279.8 1993.48   287.3 1992.71
   294.8 1993.13   316.9 1995.27   346.6 1996.68   356.4 1997.78   366.3 1999.91
   415.7 2016.43   425.6 2020.12   435.4 2024.28   445.3 2029.16   455.2 2034.52
   474.9 2045.98   494.7 2058.48   504.6 2065.12   524.3 2079.07   534.2  2086.4
#Mann= 3 , 0 , 0
       0     .13       0   279.8     .05       0   294.8     .13       0
Bank Sta=279.8,294.8
XS Rating Curve= 0 ,0
Exp/Cntr=0.3,0.1

Type RM Length L Ch R = 1 ,2748.5  ,148.3,133.8,119.3
XS GIS Cut Line= 4
     2173254.051      375414.457     2173032.823      375574.826
      2172941.18      375633.281     2172768.817      375754.328
#Sta/Elev= 30
       0 2123.96    48.8 2101.82    78.1 2087.68   107.3  2072.3   175.6 2033.64
   195.2 2023.34   214.7 2014.09   234.2 2006.14   253.7 1999.46   273.2 1994.45
   305.3 1987.86   312.8 1987.01   320.3 1987.45   362.2 1993.09   372.1 1995.91
   381.9 2000.45     412  2016.4   452.2 2035.49   472.2 2046.04   492.3 2057.56
   502.3 2063.76   512.3 2071.93   522.4 2082.84   532.4 2094.32   542.4 2104.34
   552.4 2112.68   562.5 2119.84   572.5 2126.02   582.5  2131.4   592.6 2135.33
#Mann= 3 , 0 , 0
       0     .13       0   305.3     .05       0   320.3     .13       0
Bank Sta=305.3,320.3
XS Rating Curve= 0 ,0
Exp/Cntr=0.3,0.1

Type RM Length L Ch R = 1 ,2614.6  ,187.8,186.9,185.9
XS GIS Cut Line= 4
     2173107.146      375250.601     2172936.519      375432.983
     2172870.495      375596.507     2172723.325      375729.321
#Sta/Elev= 30
       0 2124.32      20 2116.55      40  2107.9      50  2102.3    79.9 2084.44
   169.8 2034.26   179.8 2028.29   199.8  2015.5   209.8 2009.58   219.8 2004.82
   229.8 2001.01   239.8 1997.65   269.4 1988.68   288.9  1984.1   310.8 1980.68
   318.3 1979.91   328.1  1980.2   337.9 1981.76   377.1 1988.64   386.9 1991.68
   396.7 1996.64   416.3    2008   465.8 2035.74   485.6 2047.84   515.3 2067.15
   535.1 2078.09     555 2088.41   574.8 2097.78   604.5 2110.79   624.3 2119.08
#Mann= 3 , 0 , 0
       0     .13       0   310.8     .05       0   337.9     .13       0
Bank Sta=310.8,337.9
XS Rating Curve= 0 ,0
Exp/Cntr=0.3,0.1

Type RM Length L Ch R = 1 ,2427.8  ,285.6,286.2,286.7
XS GIS Cut Line= 4
     2172842.717      375133.077     2172749.281      375392.017
     2172713.689      375492.169     2172654.986      375693.453
#Sta/Elev= 30
       0 2116.54    19.7 2105.63    49.2 2088.32    98.3 2061.07   137.6 2039.62
     177 2018.99   186.8  2013.6   206.5 2001.98   216.3 1996.91   226.1 1992.92
     236 1989.79   245.8 1987.16   255.6 1984.92   275.3 1981.86   284.9 1979.63
   304.3 1974.12   313.9 1972.45   316.1 1972.38   323.6 1972.14   331.1  1972.7
   362.2 1976.62   371.9 1978.62   381.6 1982.74   401.5 1997.56   421.5 2012.03
   441.5 2025.56   461.4 2037.93   491.4 2053.48   551.3 2083.53   591.2 2102.88
#Mann= 3 , 0 , 0
       0     .13       0   316.1     .05       0   331.1     .13       0
Bank Sta=316.1,331.1
XS Rating Curve= 0 ,0
Exp/Cntr=0.3,0.1

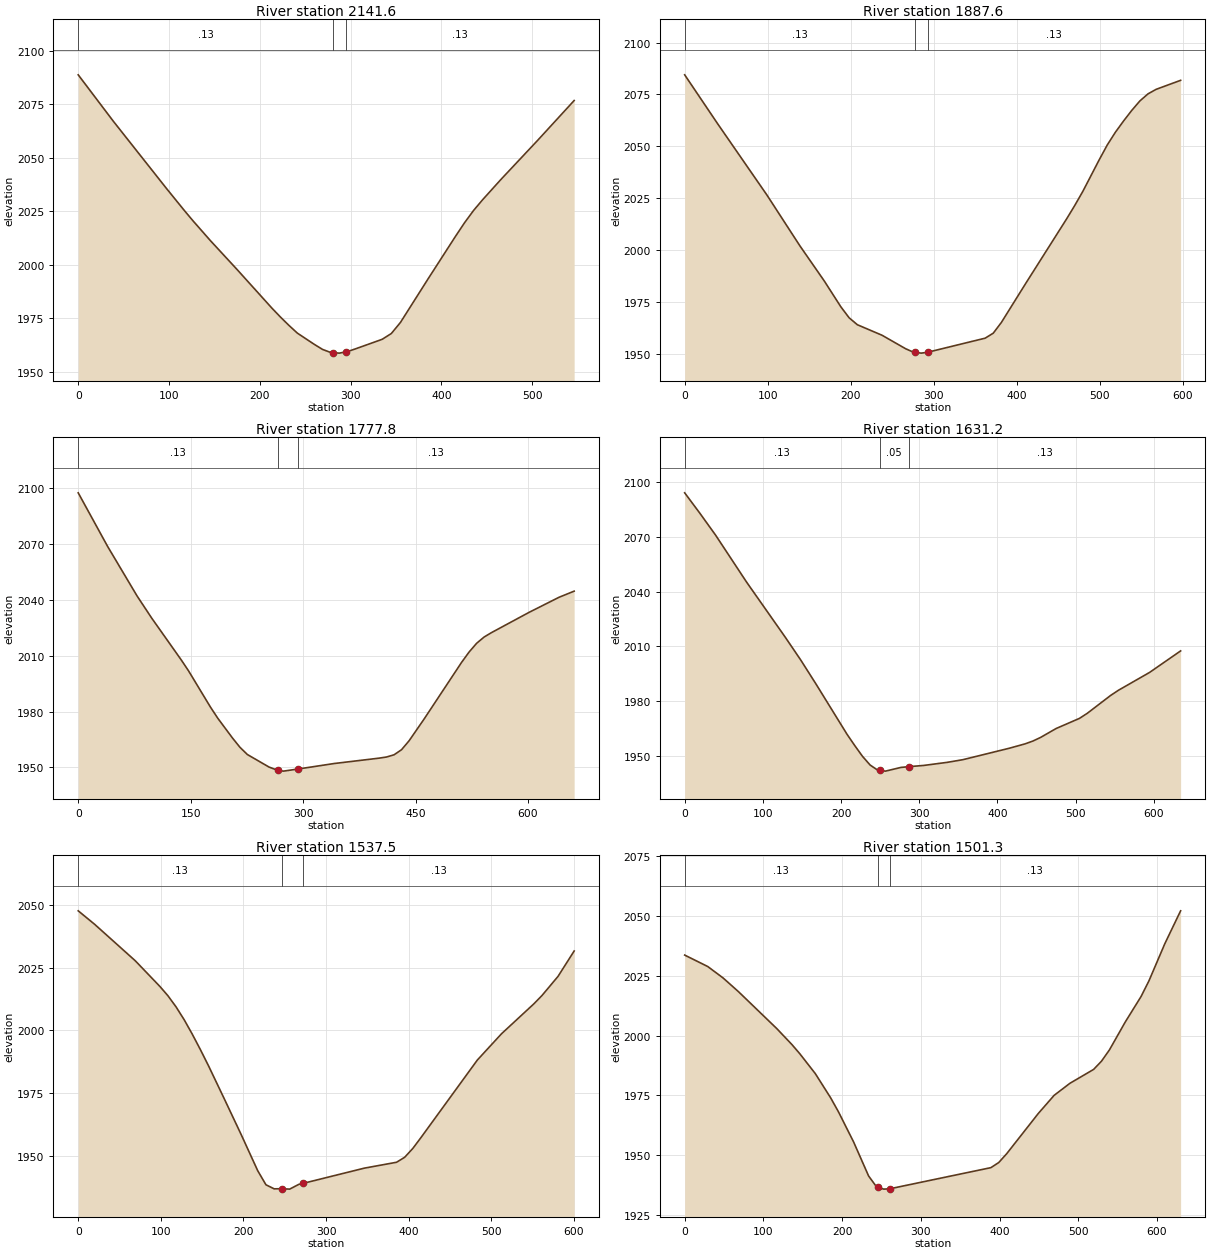
Type RM Length L Ch R = 1 ,2141.6  ,249.5,253.9,258.3
XS GIS Cut Line= 4
     2172541.771      375077.865     2172485.965      375284.061
     2172446.298      375387.947     2172380.894      375599.626
#Sta/Elev= 30
       0 2088.75    38.8 2066.99    97.1  2035.7   116.5 2025.54   126.2 2020.62
   145.6 2011.25   174.8 1997.83   213.6 1979.58   222.9 1975.47   232.2 1971.59
   241.4    1968     260 1962.76   269.2 1960.36   278.5 1958.88   280.2 1958.83
   287.8 1958.63   295.2 1959.25     297  1959.4   306.3 1960.75   334.9 1965.09
     345 1967.81     355 1972.96   385.2 1993.17   415.4 2013.06   425.5  2019.5
   435.6 2025.34   445.7 2030.41   465.8 2039.86   506.1 2058.07   546.4 2076.73
#Mann= 3 , 0 , 0
       0     .13       0   280.2     .05       0   295.2     .13       0
Bank Sta=280.2,295.2
XS Rating Curve= 0 ,0
Exp/Cntr=0.3,0.1

Type RM Length L Ch R = 1 ,1887.6  ,94.5,109.8,123.1
XS GIS Cut Line= 4
     2172359.225      375010.239     2172247.064       375219.86
     2172196.751      375300.176      2172152.67      375561.446
#Sta/Elev= 30
       0 2084.47    39.6 2060.97    99.1 2026.55   138.7 2002.14   168.4 1985.02
   188.2 1972.67   198.1 1967.42     208 1964.07   237.7 1959.01   266.2  1952.5
   275.6 1950.83   277.6 1950.74   285.1 1950.38   292.6 1950.79     362 1957.58
   371.8    1960   381.6 1965.19     411 1984.04   460.1 2015.02   469.9 2021.48
   479.7 2028.32   499.3 2043.43   509.2 2050.72     519 2056.85   528.8 2062.24
   538.6  2067.3   548.4 2071.88   558.2 2075.29     568 2077.48   597.5 2081.82
#Mann= 3 , 0 , 0
       0     .13       0   277.6     .05       0   292.6     .13       0
Bank Sta=277.6,292.6
XS Rating Curve= 0 ,0
Exp/Cntr=0.3,0.1

Type RM Length L Ch R = 1 ,1777.8  ,170.1,146.7,125.3
XS GIS Cut Line= 4
       2172256.6      374957.099     2172180.401      375179.902
     2172094.765      375222.803     2172072.059      375552.313
#Sta/Elev= 30
       0 2097.57    39.2 2068.78    78.5 2042.15    98.1  2030.2   137.4 2007.79
   147.2 2001.88   176.6 1982.29   186.4  1976.3     206 1965.69   215.8 1960.78
   225.7 1956.91   254.6 1950.17   266.3  1948.4   273.8 1947.99   292.9  1949.1
   341.3 1952.07   401.3 1954.96   411.3 1955.58   421.3 1956.76   431.3 1959.49
   441.4  1964.3   461.4 1975.97   511.4 2006.42   521.4 2011.97   531.4 2016.65
   541.4 2020.04   551.4 2022.45   601.5 2033.33   641.5 2041.44   661.6 2044.72
#Mann= 3 , 0 , 0
       0     .13       0   266.3     .05       0   292.9     .13       0
Bank Sta=266.3,292.9
XS Rating Curve= 0 ,0
Exp/Cntr=0.3,0.1

Type RM Length L Ch R = 1 ,1631.2  ,83.8,93.6,103.5
XS GIS Cut Line= 4
     2172160.106      374906.536     2172028.385       375067.11
     2172007.333      375173.369     2171850.326      375450.336
#Sta/Elev= 30
       0 2094.13    19.8 2082.72    39.6 2070.89    79.1 2045.22   128.6 2014.98
   148.4 2002.47   168.1 1989.18   207.7 1961.68   217.5 1955.53   227.4 1949.63
   237.2 1944.83   247.1 1941.96   249.4 1941.85   256.9 1941.48   276.6 1943.51
   286.5 1943.91   306.2 1944.62   335.9  1946.3   355.8 1947.75   415.5 1954.06
   435.4 1956.43   445.4 1957.97   455.3 1959.97   475.2 1964.86     505 1970.41
     515 1973.19   544.8 1982.97   554.8 1985.82   594.6 1995.59   634.4 2007.42
#Mann= 3 , 0 , 0
       0     .13       0   249.4     .05       0   286.5     .13       0
Bank Sta=249.4,286.5
XS Rating Curve= 0 ,0
Exp/Cntr=0.3,0.1

Type RM Length L Ch R = 1 ,1537.5  ,35.3,36.2,37
XS GIS Cut Line= 4
     2172055.652       374855.33     2171974.038      375035.009
     2171897.591      375139.375     2171752.096      375370.982
#Sta/Elev= 30
       0 2047.55    19.7 2042.24    69.1 2027.67    98.7 2017.52   108.5  2013.8
   118.4 2009.35   128.3 2004.19   138.1 1998.45     148 1992.25   157.9 1985.76
   177.6 1972.19   197.4 1958.41   217.2 1944.19   227.2 1938.56   237.2 1936.94
   247.1    1937  255.89 1936.83     267 1938.73  272.41 1939.14   346.2 1945.17
   385.3 1947.52   395.1  1949.5   404.9    1953   414.6 1957.24     483 1988.17
   512.3 1998.64   551.4 2010.53   561.2 2013.83   580.7 2021.47   600.2 2031.57
#Mann= 3 , 0 , 0
       0     .13       0   247.1     .05       0  272.41     .13       0
Bank Sta=247.1,272.41
XS Rating Curve= 0 ,0
Exp/Cntr=0.3,0.1

Type RM Length L Ch R = 1 ,1501.3  ,47.8,53.1,58.4
XS GIS Cut Line= 4
     2172033.765       374825.31     2171949.407      375012.168
     2171866.362      375117.124     2171686.276       375345.98
#Sta/Elev= 30
       0  2033.7    29.3 2028.92    48.8 2024.13    68.3 2018.41   117.2 2002.89
   136.7  1996.1   146.4 1992.37     166 1984.09   185.5 1973.95   195.3 1968.17
   214.6 1955.53   233.7 1941.26   243.3 1936.94   245.3 1936.69   252.8 1935.77
   260.3 1935.89   389.1 1944.76   399.1 1946.92   409.2 1950.62   449.3 1967.43
   469.4 1975.01   489.5 1980.06   519.6 1985.87   529.6 1989.32   539.7 1994.05
   559.8 2005.72   579.9 2016.39   589.9 2022.95     610 2038.44   630.1 2052.22
#Mann= 3 , 0 , 0
       0     .13       0   245.3     .05       0   260.3     .13       0
Bank Sta=245.3,260.3
XS Rating Curve= 0 ,0
Exp/Cntr=0.3,0.1

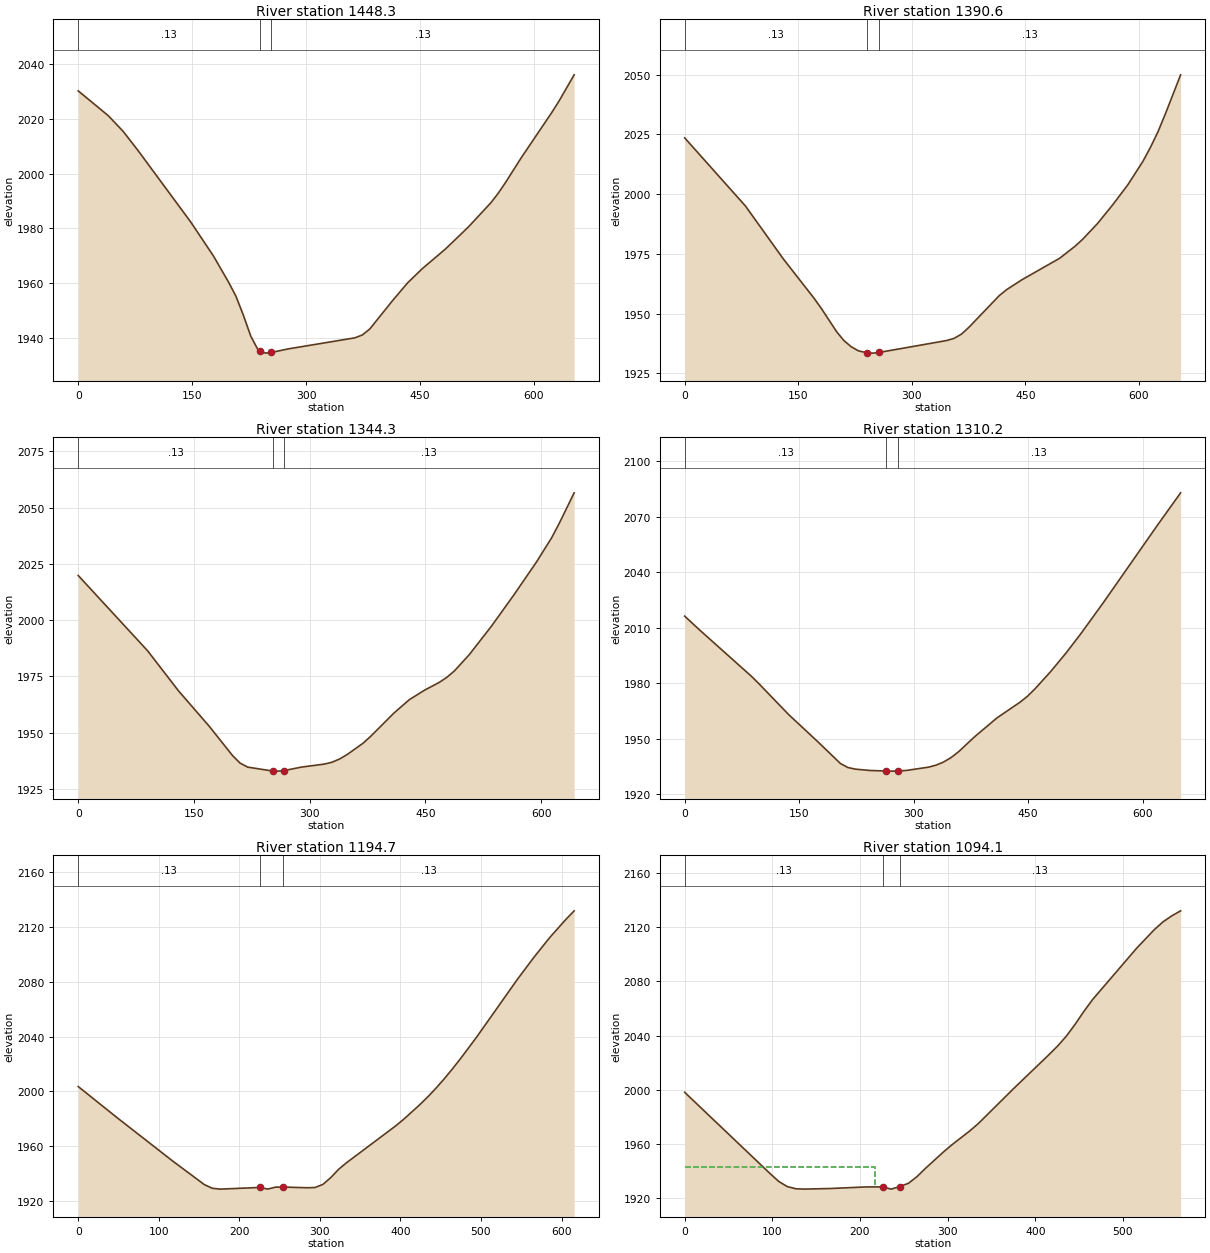
Type RM Length L Ch R = 1 ,1448.3  ,63.8,57.7,51.6
XS GIS Cut Line= 4
     2172028.982      374816.445     2171918.091      374991.965
     2171779.702       375101.12     2171587.801      375289.855
#Sta/Elev= 30
       0 2030.23    39.6 2021.17    59.3  2015.4    79.1 2008.32   148.3 1982.27
     178 1969.95   197.7  1960.5   207.6 1955.27   217.4 1948.34   227.2 1940.64
     237 1935.51   239.3 1935.26   246.8 1934.43   254.3 1934.67   276.2 1935.96
   364.3 1940.02   374.1 1941.06   383.9 1943.24   413.8 1953.58   433.7  1960.1
   453.6 1965.42   483.6 1972.48   513.5 1980.44   543.4 1989.37   553.3 1992.93
   563.3 1997.03   583.2 2005.74   623.1 2022.14   633.1 2026.52     653 2036.09
#Mann= 3 , 0 , 0
       0     .13       0   239.3     .05       0   254.3     .13       0
Bank Sta=239.3,254.3
XS Rating Curve= 0 ,0
Exp/Cntr=0.3,0.1

Type RM Length L Ch R = 1 ,1390.6  ,36.9,46.4,55.8
XS GIS Cut Line= 4
     2172019.094      374804.136     2171868.661      374937.159
     2171794.536      375037.882     2171517.829       375216.08
#Sta/Elev= 30
       0 2023.51    80.3    1995   130.5 1972.79   170.7  1956.5   180.7 1952.07
   200.8 1942.39   210.4 1938.69     220 1936.13   229.7  1934.4   241.4 1933.55
   248.9 1933.47   256.4 1933.74   345.8 1938.73   355.8 1939.64   365.8 1941.47
   375.7 1944.37   415.6 1957.57   425.6 1960.11   445.6  1964.2   495.4 1973.18
   515.4 1978.14   525.3    1981   545.3  1987.7   565.2 1995.47   585.2 2003.84
   605.1 2013.64   615.1 2019.51   625.1 2026.07     635 2033.66     655 2049.89
#Mann= 3 , 0 , 0
       0     .13       0   241.4     .05       0   256.4     .13       0
Bank Sta=241.4,256.4
XS Rating Curve= 0 ,0
Exp/Cntr=0.3,0.1

Type RM Length L Ch R = 1 ,1344.3  ,26.6,34.1,41.6
XS GIS Cut Line= 5
     2172013.918       374797.03     2171857.998      374922.106
     2171746.349      374986.712     2171663.375      375043.347
     2171488.885       375166.31
#Sta/Elev= 30
       0 2019.88      90  1986.4   129.9 1968.66   169.9 1952.84   199.9 1939.91
   209.8 1936.51   219.7 1934.72   251.9 1932.99   259.4 1932.94   266.9 1933.18
   289.2 1934.72     319 1936.07   328.9 1936.88   338.9 1938.35     349  1940.4
   369.1 1945.31   379.1 1948.41   409.2 1958.74   429.3 1964.72   448.8 1968.89
   468.2 1972.42   477.8 1974.61   487.6 1977.47     507 1984.76   536.1 1997.58
   565.2 2011.49   594.3 2026.04   613.7 2036.68   623.4 2042.99   642.8 2056.61
#Mann= 3 , 0 , 0
       0     .13       0   251.9     .05       0   266.9     .13       0
Bank Sta=251.9,266.9
XS Rating Curve= 0 ,0
Exp/Cntr=0.3,0.1

Type RM Length L Ch R = 1 ,1310.2  ,111.6,115.4,119
XS GIS Cut Line= 4
     2172008.927      374789.462     2171857.127      374911.004
      2171715.45      374939.588     2171451.754      375104.275
#Sta/Elev= 30
       0 2016.31    19.4 2008.89    87.5 1983.77    97.2 1979.82   136.1 1963.14
     175  1948.2   204.1 1936.63   213.7 1934.48   223.4 1933.59   242.6 1932.86
     264 1932.55   271.6  1932.5     279 1932.55   290.8 1932.88   319.7 1934.66
   329.4 1935.73     339 1937.37     349 1939.78     359 1943.01   379.1 1950.78
   409.2 1961.27   439.3 1969.72   449.3 1973.01   459.3  1977.1   479.4 1986.24
   499.5 1996.23   519.5 2006.99   549.6 2024.17   619.8 2065.63   649.9 2082.98
#Mann= 3 , 0 , 0
       0     .13       0     264     .05       0     279     .13       0
Bank Sta=264,279
XS Rating Curve= 0 ,0
Exp/Cntr=0.3,0.1

Type RM Length L Ch R = 1 ,1194.7  ,101.5,100.6,99.7
XS GIS Cut Line= 4
     2171995.151       374739.46     2171865.525      374808.575
     2171689.324      374815.958     2171416.038      374920.082
#Sta/Elev= 30
       0 2003.57      49 1980.56   117.5 1949.23   156.7 1932.11   166.5 1929.48
   176.3 1928.86   225.3 1930.08   235.3 1928.91   244.9 1930.29   254.7 1930.36
   284.1 1929.86   293.9 1930.02   303.7 1932.27   313.5 1937.24   323.3  1943.3
   333.3 1948.16   393.8 1974.76   403.9 1979.64   424.1 1990.37   434.2 1996.17
   444.3 2002.46   454.4 2009.18   464.4 2016.29   474.5 2023.79   494.7 2039.64
   545.1  2081.5   565.3 2097.34   585.4 2112.09   605.6 2125.39   615.7 2131.53
#Mann= 3 , 0 , 0
       0     .13       0   225.3     .05       0   254.7     .13       0
Bank Sta=225.3,254.7
XS Rating Curve= 0 ,0
Exp/Cntr=0.3,0.1

Type RM Length L Ch R = 1 ,1094.1  ,17.6,21.6,25.6
XS GIS Cut Line= 4
     2171994.131      374712.417     2171887.479      374701.943
     2171710.323       374716.63     2171430.835      374688.947
#Sta/Elev= 30
       0 1998.04    97.4 1937.96   107.2  1932.2     117 1928.33   126.9  1926.7
   136.8 1926.46   166.4  1926.9   205.9 1928.04   225.7  1928.1  235.65 1926.44
   245.4 1928.38   255.3 1930.75   265.2 1935.78     275 1941.98     295  1953.8
     305 1959.29     325 1969.35   335.1 1974.98   375.2 2000.74   415.3 2025.68
   425.4 2032.19   435.4 2039.54   445.4  2048.3   455.4 2057.85   465.5 2066.72
   515.6 2104.55   535.7 2118.29   545.7 2124.08   555.8 2128.56   565.8 2132.24
#Mann= 3 , 0 , 0
       0     .13       0   225.7     .05       0   245.4     .13       0
#XS Ineff= 2 , 0
           217.2 1942.88
Permanent Ineff=
       F       F
Bank Sta=225.7,245.4
XS Rating Curve= 0 ,0
Exp/Cntr=0.3,0.1

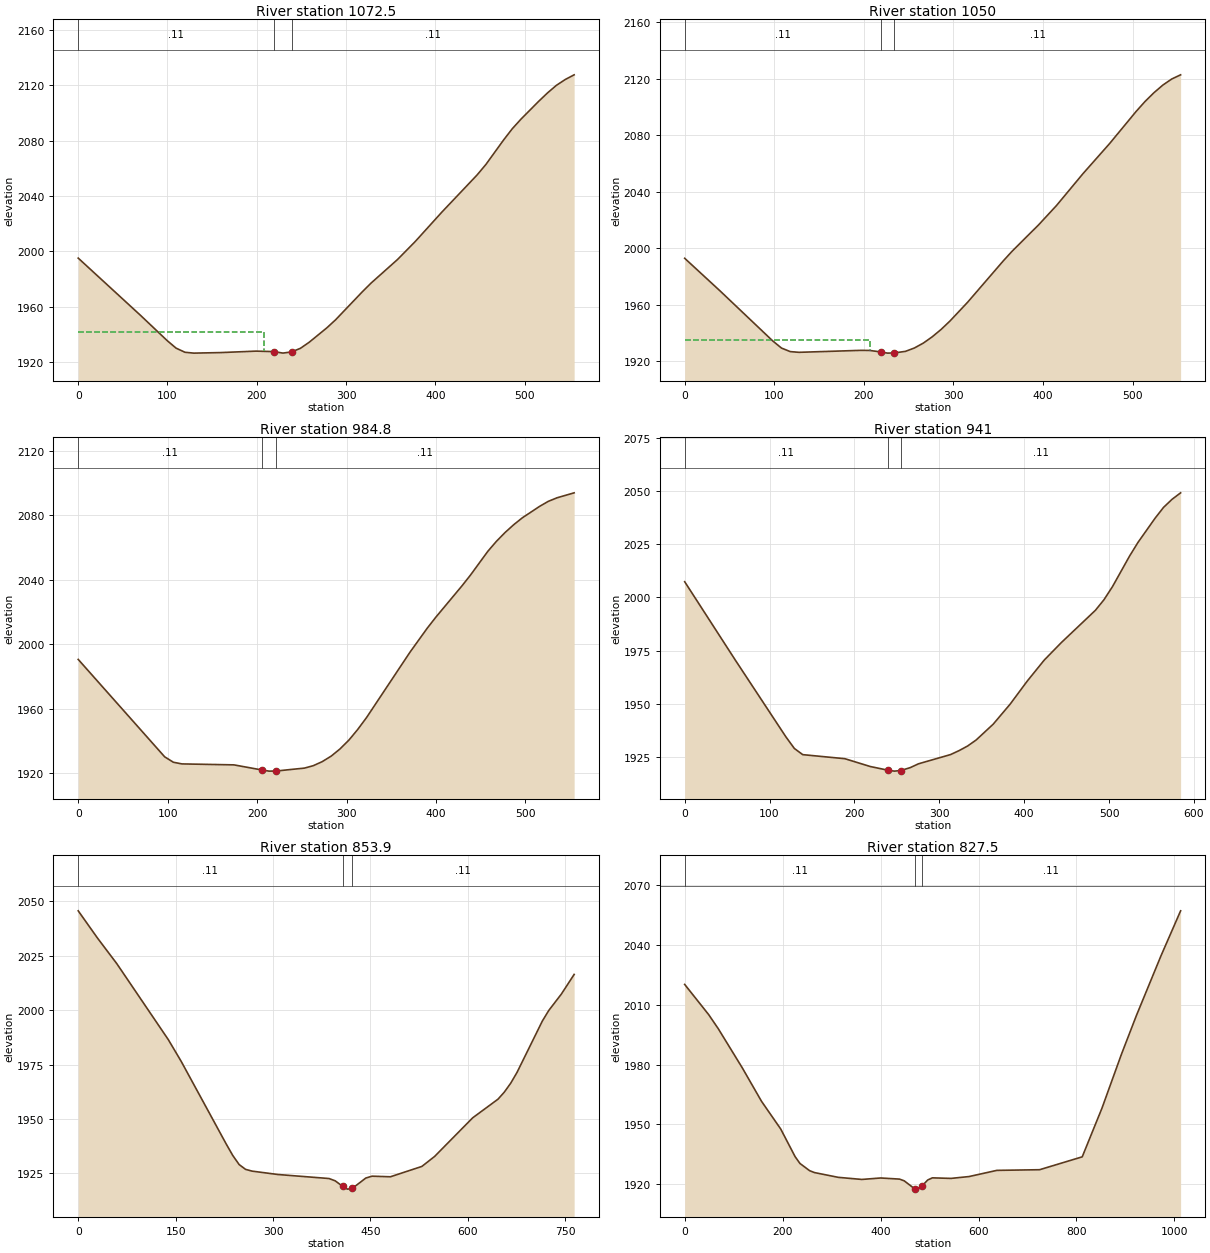
Type RM Length L Ch R = 1 ,1072.5  ,10.2,22.5,32.3
XS GIS Cut Line= 4
     2171994.469      374701.012      2171795.31      374694.318
     2171736.028      374688.612     2171442.981      374642.554
#Sta/Elev= 30
       0 1995.01    69.8 1953.63    99.6 1935.41   109.6 1929.94   119.6 1926.95
   129.5 1926.33   159.4 1926.72   199.3 1927.78   219.1 1927.42  229.32 1926.36
     239 1927.22   248.9  1929.8   258.8 1934.23   278.6 1944.66   288.5 1950.56
   318.2 1970.64     328 1976.94   357.7 1994.02   377.5    2007   407.2 2028.17
   446.7 2055.05   456.6 2062.66   476.4 2080.33   486.2 2088.52   496.1 2095.56
   515.9 2108.42   525.8 2114.49   535.7 2119.93   545.6 2124.13   555.5 2127.49
#Mann= 3 , 0 , 0
       0     .11       0   219.1    .045       0     239     .11       0
#XS Ineff= 2 , 0
          207.81 1941.28
Permanent Ineff=
       F       F
Bank Sta=219.1,239
XS Rating Curve= 0 ,0
Exp/Cntr=0.3,0.1

Type RM Length L Ch R = 1 ,1050    ,79.9,65.2,52.8
XS GIS Cut Line= 4
      2171994.22       374693.99     2171788.257      374684.891
     2171755.601      374661.141     2171454.717      374600.475
#Sta/Elev= 30
       0 1992.86    39.3 1969.87    98.2 1934.38     108 1929.29   117.8 1926.77
   127.6 1926.26   196.4 1927.65   206.2  1927.6   218.9 1926.54   226.4 1925.69
   233.9 1925.82   246.5 1926.96   256.4 1929.33   266.4 1932.81   276.2 1937.21
   286.2 1942.47     296 1948.37   315.8 1961.74   355.5 1990.96   365.4 1997.84
   395.1  2016.6   414.9 2030.17   444.6 2052.84   474.3 2074.14     504 2096.97
   513.9 2103.98   523.8 2110.15   533.7 2115.54   543.6 2119.83   553.5 2122.79
#Mann= 3 , 0 , 0
       0     .11       0   218.9    .045       0   233.9     .11       0
#XS Ineff= 2 , 0
          206.91 1935.15
Permanent Ineff=
       F       F
Bank Sta=218.9,233.9
XS Rating Curve= 0 ,0
Exp/Cntr=0.3,0.1

Type RM Length L Ch R = 1 ,984.8   ,33.6,43.8,54.1
XS GIS Cut Line= 4
     2171994.498      374685.217     2171827.524      374608.542
     2171679.014       374609.33     2171461.738      374562.506
#Sta/Elev= 30
       0  1990.6    96.7 1930.15   106.4  1926.8     116 1925.77   174.1 1925.17
   205.9 1921.96   213.4 1921.29   220.9 1921.34     253 1923.17   262.9 1924.68
   272.8 1927.17   282.8 1930.58   292.6 1935.01   302.6 1940.51   312.4 1947.06
   322.4 1954.54   370.9 1995.04   390.2 2009.94   399.9 2016.83   428.9 2036.12
   438.6 2042.93   457.9 2057.61   467.5 2063.81   477.2  2069.3   486.9 2074.16
   496.5 2078.43   515.9 2085.57   525.5 2088.64   535.2 2090.85   554.5 2093.96
#Mann= 3 , 0 , 0
       0     .11       0   205.9    .045       0   220.9     .11       0
Bank Sta=205.9,220.9
XS Rating Curve= 0 ,0
Exp/Cntr=0.3,0.1

Type RM Length L Ch R = 1 ,941     ,98.4,87,75.7
XS GIS Cut Line= 4
     2172035.497      374663.608     2171830.873      374586.691
     2171745.544      374545.607     2171475.742      374520.494
#Sta/Elev= 30
       0 2007.35    59.6 1970.58   119.2 1934.53   129.2 1929.05   139.1 1926.14
   188.8 1924.23   218.6 1920.57   239.5 1918.83     247  1918.4   254.5 1918.67
     266 1920.08   275.4 1921.83   313.3 1926.18   323.3 1928.03   333.4 1930.21
   343.4 1933.02   363.5 1940.45   383.6 1949.93   403.6 1960.68   423.7 1970.58
   443.8 1978.78   483.9 1993.92     494 1998.89     504 2005.02   524.1 2019.35
   534.1 2025.82   554.2 2037.16   564.2 2042.26   574.2 2046.04   584.3 2049.09
#Mann= 3 , 0 , 0
       0     .11       0   239.5    .045       0   254.5     .11       0
Bank Sta=239.5,254.5
XS Rating Curve= 0 ,0
Exp/Cntr=0.3,0.1

Type RM Length L Ch R = 1 ,853.9   ,25.8,26.4,27.1
XS GIS Cut Line= 4
     2172188.553      374632.549     2171844.502      374478.798
     2171731.199      374484.193     2171457.749      374480.341
#Sta/Elev= 30
       0 2045.61    29.8 2033.06    59.5 2021.32   138.8 1986.43   158.7 1976.42
   228.1 1938.43     238 1933.27   247.9 1929.06   257.8 1926.86   267.8 1926.06
   307.4 1924.51   386.3 1922.66   395.8  1921.6   407.2 1919.07   414.6 1917.79
   422.2 1918.14     443 1922.89   452.5 1923.74   480.8 1923.46   529.3 1928.22
   548.9  1932.8   607.5 1950.53   646.6 1959.12   656.3 1962.36   666.1 1966.44
   675.8 1971.39   714.9 1995.04   724.7 1999.84   744.2 2007.42   763.8  2016.4
#Mann= 3 , 0 , 0
       0     .11       0   407.2    .045       0   422.2     .11       0
Bank Sta=407.2,422.2
XS Rating Curve= 0 ,0
Exp/Cntr=0.3,0.1

Type RM Length L Ch R = 1 ,827.5   ,76.7,72.3,67.9
XS GIS Cut Line= 6
     2172242.293      374598.609     2171961.987      374457.576
     2171750.778      374455.586     2171667.764      374448.101
      2171468.74      374406.711     2171277.936      374469.729
#Sta/Elev= 30
       0 2020.25      49  2005.1    68.6 1998.02   117.7 1978.36   156.9  1961.6
   196.1  1947.7   225.5 1933.82   235.3 1930.43     255  1926.8   264.8 1925.85
   313.8 1923.44   361.8 1922.39   400.2 1923.12   438.7 1922.56   448.3 1921.68
   469.6 1917.69   477.1 1917.53   484.6 1919.11   496.3 1922.12   505.8 1923.19
   543.6 1922.91   580.6 1923.84   637.4 1926.94   724.6 1927.27   811.7 1933.73
   851.9 1958.08     892 1985.35   922.2 2004.56   972.4 2034.54  1012.6 2057.18
#Mann= 3 , 0 , 0
       0     .11       0   469.6    .045       0   484.6     .11       0
Bank Sta=469.6,484.6
XS Rating Curve= 0 ,0
Exp/Cntr=0.3,0.1

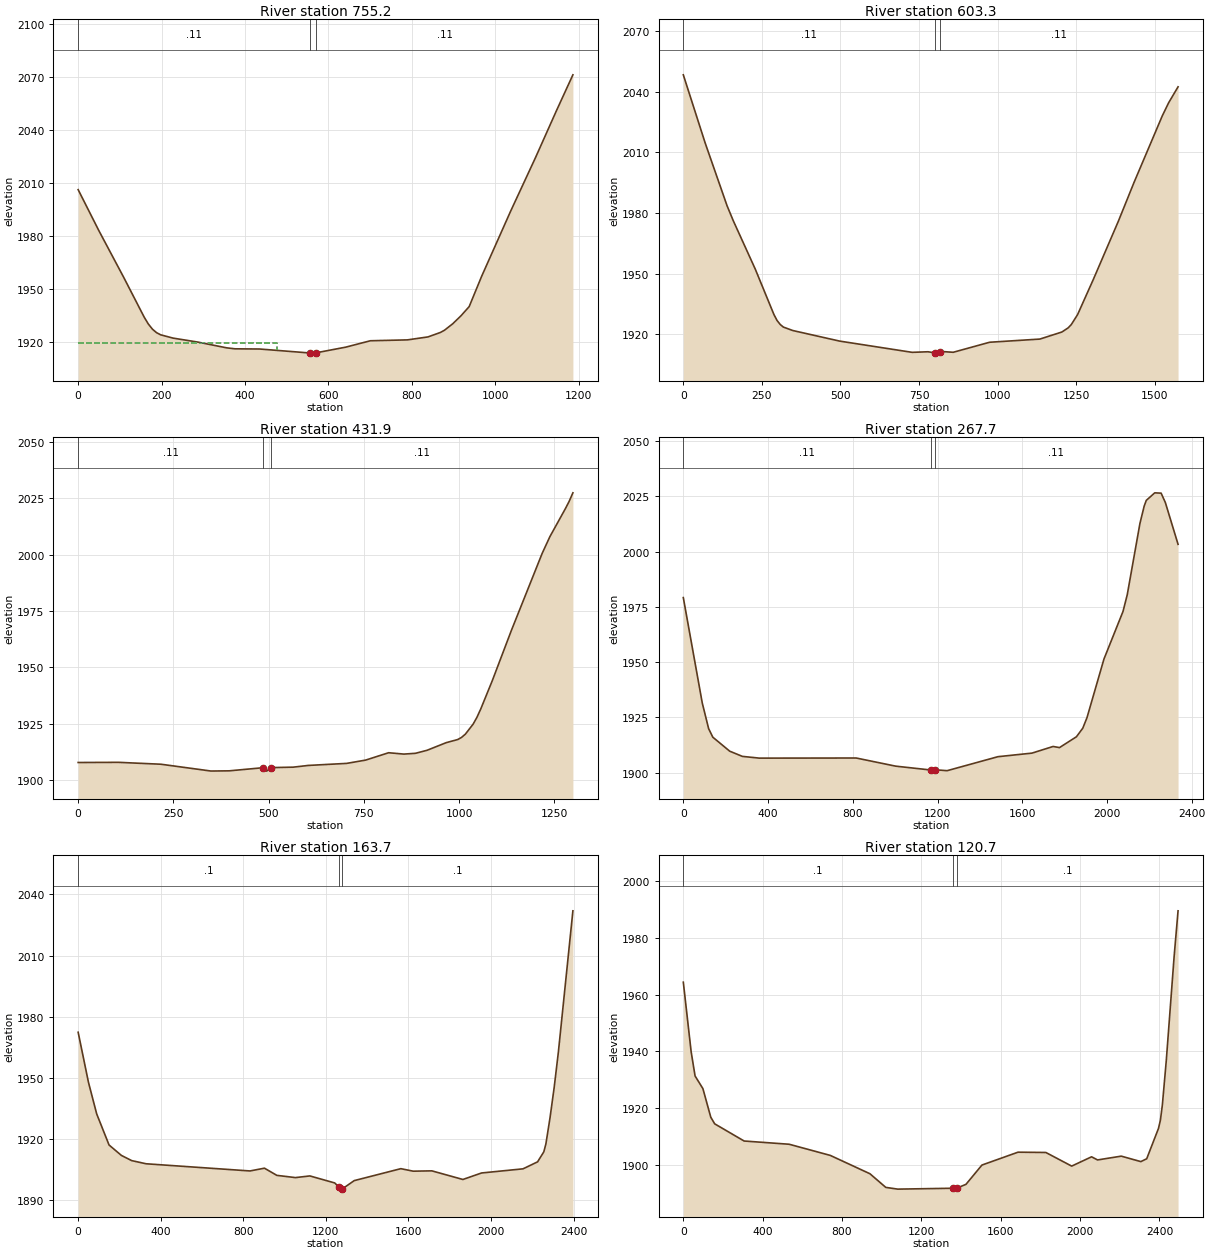
Type RM Length L Ch R = 1 ,755.2   ,154.9,151.9,149
XS GIS Cut Line= 5
     2172271.027      374575.754     2171977.203      374341.418
     2171659.961      374409.725     2171423.367      374399.243
     2171181.659      374457.476
#Sta/Elev= 30
       0    2006    49.4  1982.9   108.8 1956.52   158.2 1933.85   168.1 1929.96
     178 1927.02   187.9 1925.03   197.8 1923.81   227.5 1921.94   286.8 1919.69
     356 1916.43   375.8 1915.88   434.8 1915.77   555.2 1913.52   562.7 1913.44
   570.2 1913.62   641.3 1916.82   700.3 1920.44   789.2 1920.94   838.5 1922.62
   868.1 1925.13     878  1926.4   897.7 1930.05   917.4 1934.54   937.2 1939.78
     967  1956.9  1036.6 1993.83  1096.3 2024.22    1146 2050.52  1185.8 2071.02
#Mann= 3 , 0 , 0
       0     .11       0   555.2    .045       0   570.2     .11       0
#XS Ineff= 2 , 0
          476.51 1919.13
Permanent Ineff=
       F       F
Bank Sta=555.2,570.2
XS Rating Curve= 0 ,0
Exp/Cntr=0.3,0.1

Type RM Length L Ch R = 1 ,603.3   ,174.2,171.4,168.6
XS GIS Cut Line= 6
     2172436.265      374616.094     2171978.621      374335.038
     2171838.808       374205.02     2171724.814      374245.709
       2171695.9      374367.797     2171097.635      374406.711
#Sta/Elev= 30
       0 2048.29    69.6 2014.54   139.2 1983.52   159.1 1976.06   228.8 1952.22
   288.4 1929.67   298.4 1926.72   308.3 1924.78   318.3  1923.5   348.1  1921.8
   497.3 1916.56     728    1911   778.4 1911.28   801.2 1910.71   808.7 1910.61
   816.2 1910.94   828.8 1911.34   858.7 1911.03   974.5 1915.99  1134.4 1917.56
  1204.3 1921.05  1224.3  1923.1  1234.3 1924.73  1254.3 1929.65  1304.2 1946.98
  1384.2 1975.92  1434.1 1995.12    1524 2028.05    1544 2034.46    1574 2042.35
#Mann= 3 , 0 , 0
       0     .11       0   801.2    .045       0   816.2     .11       0
Bank Sta=801.2,816.2
XS Rating Curve= 0 ,0
Exp/Cntr=0.3,0.1

Type RM Length L Ch R = 1 ,431.9   ,161.5,164.2,165.2
XS GIS Cut Line= 6
     2172153.102      374172.103     2172123.488       374124.72
     2171851.711      374015.829     2171654.953      374101.393
     2171556.639      374331.859     2171075.964      374387.264
#Sta/Elev= 30
       0 1907.81   106.4 1907.88   217.4 1907.04   348.7 1904.02   396.8 1904.11
   485.6  1905.5  495.01 1903.98   505.4 1905.54   564.6 1905.74   604.6 1906.51
   704.9 1907.41     755 1908.88   815.1 1912.14   855.4 1911.54   885.7 1911.89
   915.9 1913.22   966.3 1916.61   996.6    1918  1006.6 1918.94  1016.7  1920.4
  1036.9  1924.8    1047 1927.85    1057 1931.53  1087.3 1944.11  1137.7 1966.52
  1218.3 2000.61  1238.5 2008.02  1278.8 2020.32  1288.9 2023.61    1299 2027.49
#Mann= 3 , 0 , 0
       0     .11       0   485.6    .045       0   505.4     .11       0
Bank Sta=485.6,505.4
XS Rating Curve= 0 ,0
Exp/Cntr=0.3,0.1

Type RM Length L Ch R = 1 ,267.7   ,92.9,104,112.1
XS GIS Cut Line= 6
     2172610.065      374488.985     2172448.881      374191.184
      2171751.56      373902.619     2171582.526      373952.081
     2171477.275      374328.864     2170817.555       374331.44
#Sta/Elev= 30
       0 1979.17    89.6 1931.45   119.5 1919.91   139.4 1916.03   219.1 1909.71
   278.9 1907.36   358.6 1906.57   816.2 1906.62  1002.6 1902.94  1167.2 1901.21
 1178.22 1900.69  1186.8 1901.31  1245.5 1900.89  1485.3 1907.22  1645.8 1908.83
  1745.8 1911.84  1775.8 1911.33  1855.8 1916.23  1885.8  1920.1  1905.8 1924.91
  1985.7 1951.36  2075.7  1972.9  2095.7 1980.45  2155.7 2012.76  2175.6 2020.53
  2185.6 2023.14  2225.6 2026.56  2255.6 2026.41  2275.6 2022.18  2335.6 2003.28
#Mann= 3 , 0 , 0
       0     .11       0  1167.2    .045       0  1186.8     .11       0
Bank Sta=1167.2,1186.8
XS Rating Curve= 0 ,0
Exp/Cntr=0.3,0.1

Type RM Length L Ch R = 1 ,163.7   ,45.4,43.1,43.7
XS GIS Cut Line= 6
     2172713.344      374481.983     2172481.153      374157.349
        2172220.      373984.455     2171659.444      373815.646
     2170954.094      373928.826     2170619.749      374114.378
#Sta/Elev= 30
       0 1972.44    49.9 1947.92    89.8  1932.4   149.7 1917.16   209.5 1912.05
   259.4  1909.5   329.3 1907.95   832.4 1904.43   902.4 1905.79   962.4 1902.27
  1052.4 1901.17  1122.4 1901.99  1242.5 1898.56  1263.9  1896.5  1271.4 1895.52
  1278.9 1895.57  1337.2 1899.69    1563 1905.55    1623 1904.32  1713.3 1904.48
  1863.7 1900.25    1954 1903.44    2155 1905.47  2225.5  1908.9  2255.7 1913.83
  2265.7 1917.69  2285.8 1930.58    2306 1945.53  2326.1 1962.69  2396.5 2031.98
#Mann= 3 , 0 , 0
       0      .1       0  1263.9    .045       0  1278.9      .1       0
Bank Sta=1263.9,1278.9
XS Rating Curve= 0 ,0
Exp/Cntr=0.3,0.1

Type RM Length L Ch R = 1 ,120.7   ,54.1,53.3,52.5
XS GIS Cut Line= 6
     2172758.857      374460.977     2172276.903      373860.168
     2171638.997       373771.82     2171367.613      373849.825
      2170908.97      373897.414     2170614.497      374058.362
#Sta/Elev= 30
       0 1964.34    39.5 1939.91    59.3 1931.38    98.8 1926.93   138.4  1916.9
   158.1 1914.57   306.4 1908.53   533.6 1907.39   740.8 1903.47   940.5 1897.03
  1020.6 1892.23  1080.6 1891.62  1359.2 1891.93  1377.6 1891.94  1424.6  1893.3
  1505.2 1900.08  1686.8  1904.6  1827.2  1904.5  1957.5 1899.71  2057.7 1902.98
  2087.8 1901.88  2207.3 1903.21    2306 1901.29  2335.6 1902.29  2394.8 1912.93
  2404.7 1915.87  2414.6 1921.27  2434.3 1936.84  2473.8 1973.39  2493.6 1989.42
#Mann= 3 , 0 , 0
       0      .1       0  1359.2    .045       0  1377.6      .1       0
Bank Sta=1359.2,1377.6
XS Rating Curve= 0 ,0
Exp/Cntr=0.3,0.1

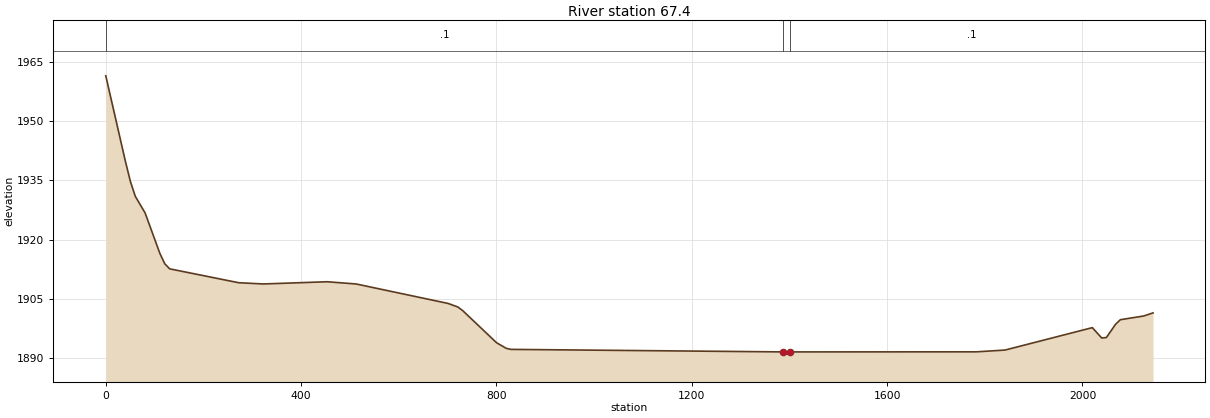
Type RM Length L Ch R = 1 ,67.4    ,66.4,67.4,68.4
XS GIS Cut Line= 6
      2172804.37       374436.47     2172538.562      374081.848
     2172272.631      373761.479     2171497.797      373711.081
     2171125.307      373750.839     2171001.543      373801.761
#Sta/Elev= 30
       0 1961.47    40.3 1939.75    50.4 1934.73    60.4 1930.96    80.6 1926.72
   110.8 1916.48   120.9 1913.85   130.9 1912.58     272 1909.07   322.3 1908.75
   453.1 1909.31   512.6 1908.75   700.9 1903.82   720.8 1902.93   730.7 1902.02
   800.1 1893.88   819.9 1892.45   829.8 1892.18  1386.5 1891.54 1394.51 1890.98
  1401.5 1891.54  1782.7 1891.56  1841.4 1892.01  2020.2 1897.69  2039.3 1895.07
  2048.9 1895.18    2068 1898.58  2077.6  1899.7  2125.4 1900.64  2144.5 1901.43
#Mann= 3 , 0 , 0
       0      .1       0  1386.5    .045       0  1401.5      .1       0
Bank Sta=1386.5,1401.5
XS Rating Curve= 0 ,0
Exp/Cntr=0.3,0.1

Chan Stop Cuts=-1
Use User Specified Reach Order=0
Composite Channel Slope=5